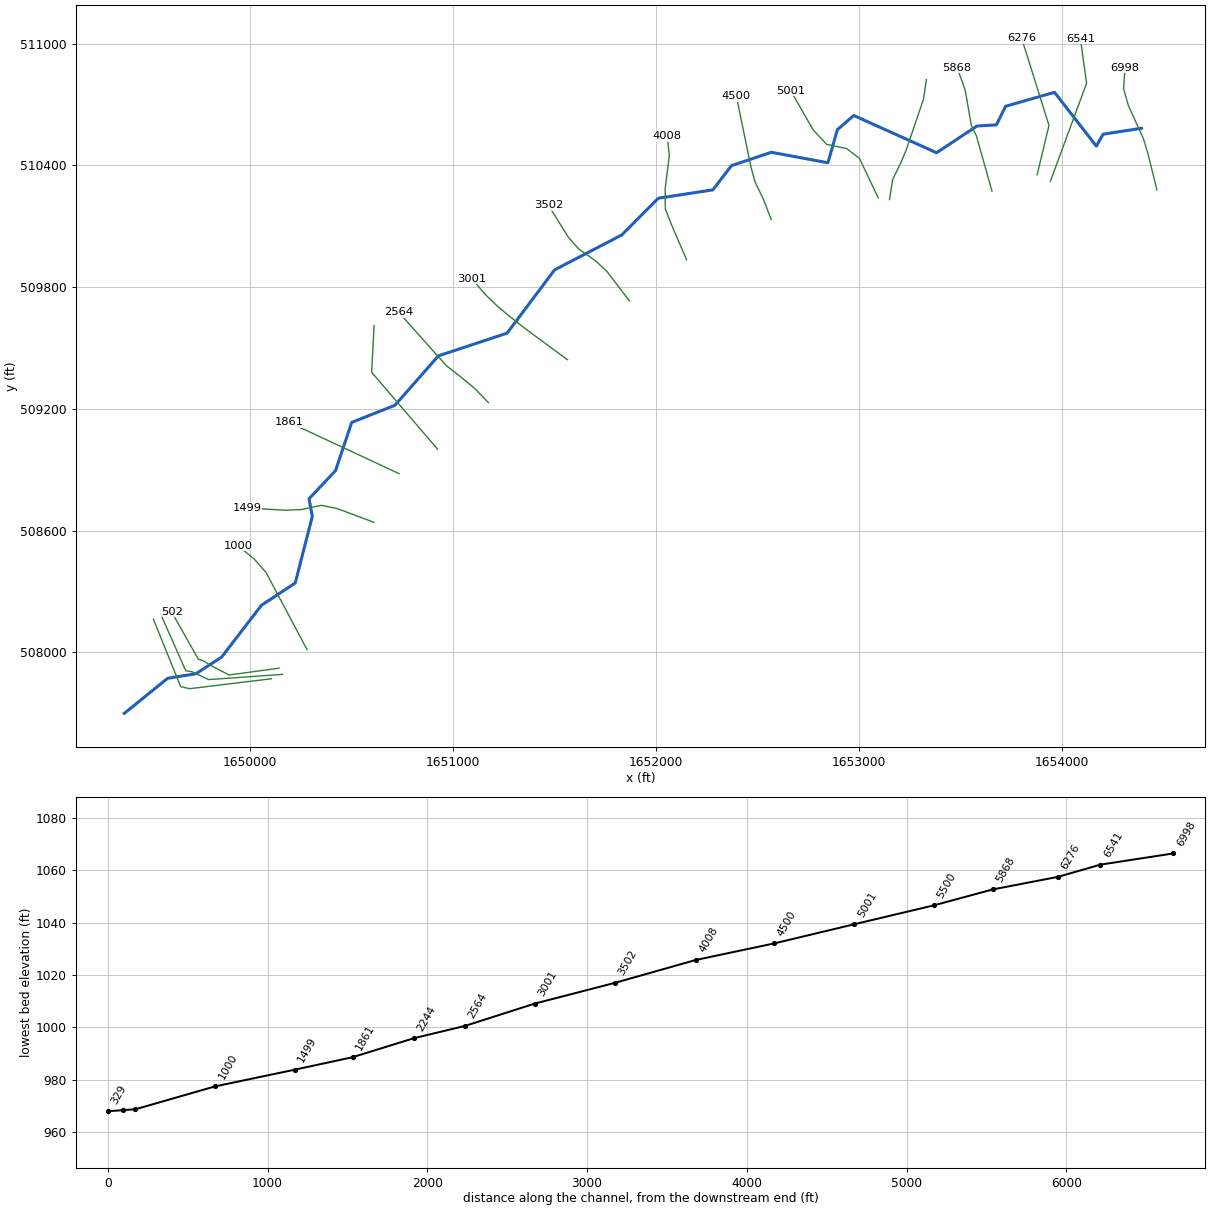
--- WhitneyRn.prj (project) ---

Proj Title=WhitneyRn
Current Plan=p01
Default Exp/Contr=0,0
English Units
Geom File=g01
Flow File=f01
Plan File=p01
BEGIN DESCRIPTION:
---------- MODELED AS PART OF WVEM CTP PROGRAM, 2025----------
Stream Name: Whitney Run
Flood Zone: AFH
Marshall County, WV
HEC-RAS Version: RAS 6.6
Vertical Datum: NAVD88
Projection: NAD 1983 StatePlane West Virginia N FIPS 4701 (US Feet)
Terrain: 1-meter West Virginia FEMA R3 South Central (collected 2018-2019)
Land Use: 2024 NLCD
Hydrologic Method:
Duda et al., "Estimation of magnitude and frequency of floods for rural, unregulated streams in and near Virginia and West Virginia." September 8, 2025.
Additional Model Notes:
None
END DESCRIPTION:
DSS File=dss
DSS Export Rating Curves= 0
DSS Export Rating Curve Sorted= 0
DSS Export Volume Flow Curves= 0
DXF OffsetX= 0
DXF OffsetY= 0
DXF ScaleX= 0
DXF ScaleY= 0

--- WhitneyRn.p01 (plan) ---

Plan Title=Floodplain
Program Version=6.60
Short Identifier=Floodplain
Geom File=g01
Flow File=f01
Subcritical Flow
K Sum by GR= 0
Std Step Tol= 0.01
Critical Tol= 0.01
Num of Std Step Trials= 20
Max Error Tol= 0.3
Flow Tol Ratio= 0.001
Split Flow NTrial= 30
Split Flow Tol= 0.02
Split Flow Ratio= 0.02
Log Output Level= 0
Friction Slope Method= 1
Unsteady Friction Slope Method= 2
Unsteady Bridges Friction Slope Method= 1
Parabolic Critical Depth
Global Vel Dist= 0 , 0 , 0
Global Log Level= 0
CheckData=True
Encroach Param=-1 ,0,0, 0
Flow Ratio Tolerance=0.1
Flow Ratio Min Ratio=0.5
Flow Ratio Max Ratio=4
Flow Ratio Max Iterations= 10
Computation Interval=1MIN
Output Interval=1HOUR
Instantaneous Interval=1HOUR
Mapping Interval=1HOUR
Computation Time Step Use Courant=        0
Computation Time Step Use Time Series=    0
Computation Time Step Count To Double=0
Computation Time Step Max Doubling=0
Computation Time Step Max Halving=0
Computation Time Step Residence Courant=0
Run HTab= 0
Run UNet= 0
Run Sediment= 0
Run PostProcess= 0
Run WQNet= 0
Run RASMapper=-1
UNET Theta= 1
UNET Theta Warmup= 1
UNET ZTol= 0.02
UNET ZSATol= 0.02
UNET MxIter= 20
UNET Max Iter WO Improvement= 0
UNET MaxInSteps= 0
UNET DtIC= 0
UNET DtMin= 0
UNET MaxCRTS= 20
UNET WFStab= 2
UNET SFStab= 1
UNET WFX= 1
UNET SFX= 1
UNET Gravity=32.17405
UNET 1D Methodology=Finite Difference
UNET DSS MLevel= 4
UNET Pardiso=0
UNET DZMax Abort= 100
UNET Use Existing IB Tables=-1
UNET Froude Reduction=False
UNET Froude Limit= 0.8
UNET Froude Power= 4
UNET D1 Cores= 0
UNET WindReference=Eulerian
UNET WindDragFormulation=Hsu (1988)
UNET D2 Coriolis=0
UNET D2 Cores= 0
UNET D2 Theta= 1
UNET D2 Theta Warmup= 1
UNET D2 Z Tol= 0.01
UNET D2 Volume Tol= 0.01
UNET D2 Max Iterations= 20
UNET D2 Advanced Convergence=0
UNET D2 WS Max Tol=0.15
UNET D2 WS RMS Tol=0.002
UNET D2 WS Stall Tol=1
UNET D2 Equation= 0
UNET D2 RampUpFraction=0.1
UNET D2 TimeSlices= 1
UNET D2 Turbulence Formulation=None
UNET D2 Eddy Viscosity=0.3
UNET D2 Transverse Eddy Viscosity=0.1
UNET D2 Smagorinsky Mixing=0.05
UNET D2 BCVolumeCheck=0
UNET D2 Cores=0
UNET D2 SolverType=PARDISO (Direct)
UNET D2 Minimum Iterations= 3
UNET D2 Maximum Iterations= 30
UNET D2 Restart Number= 10
UNET D2 Relaxation Coeff=1.3
UNET D2 SOR Precondition Iterations= 10
UNET D2 ILUT Maximum Fill= 8
UNET D2 ILUT Tolerance=1E-08
UNET D2 Convergence Tolerance=0.00001
PS Theta= 1
PS WS Tol= 0.01
PS Volume Tol= 0.01
PS Max Iterations= 20
PS Equation= 0
PS Advance Time Step=-1
PS Target Courant=0.9
PS Time Slices= 1
PS Iterate With 2D=0
PS Project Initial WSE from DS=-1
PS Ramp Up Initial WSE from US=-1
PS Cores=0
UNET D1D2 MaxIter= 0
UNET D1D2 ZTol=0.01
UNET D1D2 QTol=0.1
UNET D1D2 MinQTol=1
Write IC File= 0
Write IC File at Fixed DateTime=0
Write IC File at Sim End=0
Echo Input=False
Echo Parameters=False
Echo Output=False
Write Detailed= 0
HDF Write Warmup=0
HDF Write Time Slices=0
HDF Flush=0
HDF Compression= 1
HDF Chunk Size= 1
HDF Spatial Parts= 1
HDF Use Max Rows=0
HDF Fixed Rows= 1
Calibration Method= 0
Calibration Iterations= 20
Calibration Max Change=0.05
Calibration Tolerance=0.2
Calibration Maximum=1.5
Calibration Minimum=0.5
Calibration Optimization Method= 1
WQ AD Non Conservative
WQ ULTIMATE=-1
WQ Max Comp Step=1HOUR
WQ Output Interval=15MIN
WQ Output Selected Increments= 0
WQ Create Restart=0
WQ Fixed Restart=0
WQ System Summary=0
WQ Write To DSS=0
Sorting and Armoring Iterations= 10
XS Update Threshold= 0.02
Bed Roughness Predictor= 0
Processes Affected by Predictor=Sediment Only
Hydraulics Update Threshold= 0.02
Energy Slope Method= 1
Volume Change Method= 1
Sediment Retention Method= 0
Sediment TS Multiplier= 1
Warm Up Method= 0
XS Weighting Method= 0
Number of US Weighted Cross Sections= 1
Number of DS Weighted Cross Sections= 1
Upstream XS Weight=0
Main XS Weight=1
Downstream XS Weight=0
Number of DS XS's Weighted with US Boundary= 1
Upstream Boundary Weight= 1
Weight of XSs Associated with US Boundary= 0
Number of US XS's Weighted with DS Boundary= 1
Downstream Boundary Weight= 0.5
Weight of XSs Associated with DS Boundary= 0.5
Percentile Method= 0
Sediment Output Level= 3
Mass or Volume Output= 0
Output Increment Type= 1
Profile and TS Output Increment= 1
Transport Output Increment 1
XS Output Flag= 0
XS Output Increment= 10
Read HDF5 Sediment Hotstart= 0
Sediment Hotstart Type= 0
Write Gradation File= 0
Read Gradation Hotstart= 0
Write HDF5 File= 1
Write Binary Output= 1
Write DSS Sediment File= 0
DSS Sediment Output Type= 1
SV Curve= 0
Specific Gage Flag= 0
Subcell Erosion Methods= 0
Subcell Deposition Methods= 0
Advection Scheme= 1
Matrix Solver= 0
Implicit Weighting Factor= 1
Maximum Outer Loop Convergence Iterations= 5
Convergence Maximum Absolute= 0.001
Convergence RMSE= 0.0001
Grain Fractions Max Abs Error= 0.001
Max Subgrid Regions= 1
Max Subgrid Length Scale= 3.402823E+38
Initial Layer Thickness= 3
Min Layer Thickness= 0.1
Max Layer Thickness= 6
Number of Layers= 5

--- WhitneyRn.f01 (steady flow) ---

Flow Title=Flow
Program Version=6.60
BEGIN FILE DESCRIPTION:
Flow
END FILE DESCRIPTION:
Number of Profiles= 1
Profile Names=P100yr
River Rch & RM=WhitneyRn,Main            ,6998
     849
River Rch & RM=WhitneyRn,Main            ,1861
    1130
Boundary for River Rch & Prof#=WhitneyRn,Main            , 1
Up Type= 0
Dn Type= 3
Dn Slope=0.022
DSS Import GetInterval= 0
DSS Import GetPeak= 0
DSS Import FillOption= 0

--- WhitneyRn.g01 (geometry) ---

Geom Title=Geometry
Program Version=6.60

River Reach=WhitneyRn       ,Main
Reach XY= 30
     1654394.541      510583.509     1654204.941       510554.01
     1654171.702      510495.149     1653965.344      510760.506
     1653724.206      510691.691     1653678.935       510599.99
      1653583.33      510594.528     1653384.027      510462.741
     1652975.682      510646.248     1652894.965      510576.351
     1652848.223      510413.186     1652569.285      510464.905
     1652372.647      510398.895     1652281.041      510279.668
     1652011.841      510238.335     1651832.662      510057.642
     1651500.706      509885.172     1651266.779      509573.341
     1650928.331      509461.463     1650713.447      509217.581
     1650500.698      509133.181     1650420.709      508895.467
     1650290.247      508756.781     1650306.344      508669.928
     1650222.237      508341.623      1650055.42        508231.5
     1649859.207      507976.154     1649732.125      507893.911
     1649593.102      507871.605     1649379.548       507698.73

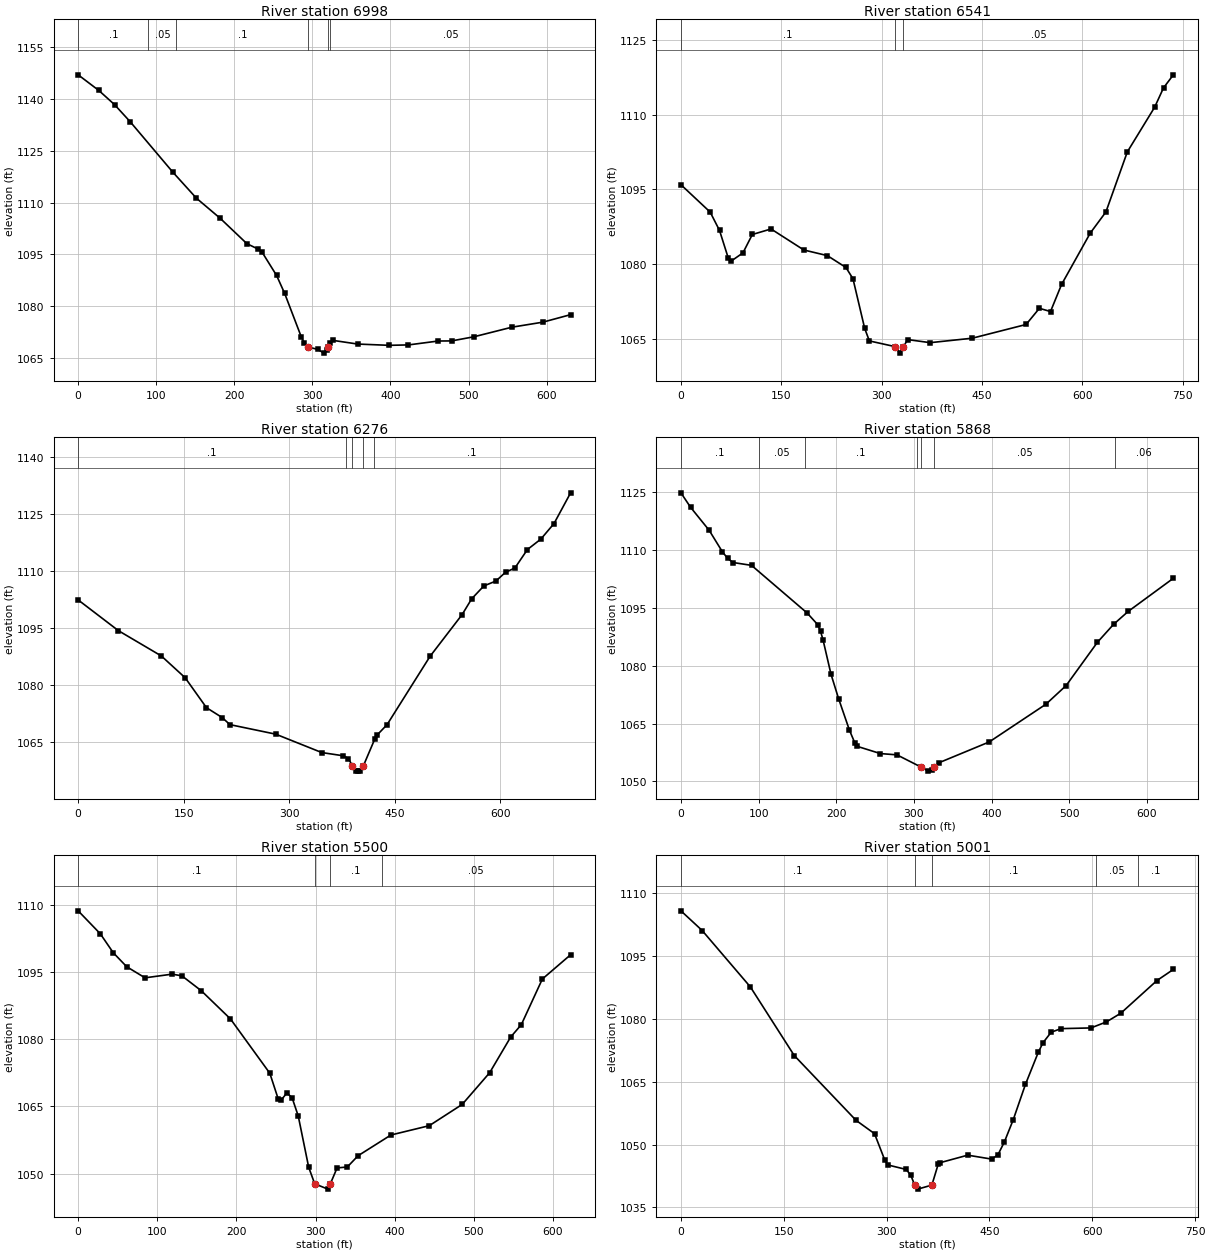
Type RM Length L Ch R = 1 ,6998    ,459.5,457.3,450
XS GIS Cut Line= 6
1654470.13810605510279.6719954761654425.65361497510459.849456638
1654402.91678381 510533.663285391654330.34540664 510693.24334681
1654306.15024506510777.8583350631654312.89432606  510882.2295174
#Sta/Elev= 30
       0 1147.03    26.4 1142.51    46.6 1138.39    66.7 1133.42   120.9 1118.91
   151.4 1111.29   181.9 1105.45   216.1  1098.1   230.4 1096.54   235.7 1095.58
   254.1  1088.9   264.5 1083.67   285.9    1071   289.5 1069.38  294.981068.142
   306.6 1067.47   314.8 1066.38   318.4 1067.31  319.921068.141     322 1069.21
   326.4 1070.07     358 1069.01   398.2 1068.64     423 1068.76   461.2 1069.89
   478.3 1069.92   506.9 1071.12   555.6  1073.9   595.1 1075.35   630.7 1077.53
#Mann= 6, -1 ,  0
       0     0.1       0      90    0.05       0  125.69     0.1       0
  294.98   0.045       0  319.92     0.1       0  322.83    0.05       0
Bank Sta=294.98,319.92
XS Rating Curve= 0 ,0
Exp/Cntr(USF)=0,0
Exp/Cntr=0.3,0.1

Type RM Length L Ch R = 1 ,6541    ,257.4,264.7,268.4
XS GIS Cut Line= 3
1653945.52782496510323.3460444721654123.56539478 510804.89528093
1654093.04466852511025.322748323
#Sta/Elev= 30
       0 1095.91    43.7 1090.41    57.7 1086.72    70.6 1081.25    75.2 1080.58
    92.7 1082.22   106.7 1085.91   134.7 1087.02   183.7  1082.8   218.8 1081.67
   246.6 1079.29   257.1 1077.03   274.6 1067.06   281.6 1064.54  320.661063.378
   327.1 1062.09  332.571063.378   338.8 1064.81   372.5 1064.19   435.5 1065.09
   515.8 1067.84   535.7 1071.09   552.3 1070.44   568.8 1075.87   611.7 1086.19
   635.1 1090.44   667.1  1102.5   707.9 1111.46   721.2 1115.36   735.9 1117.97
#Mann= 3, -1 ,  0
       0     0.1       0  320.66   0.045       0  332.57    0.05       0
Bank Sta=320.66,332.57
XS Rating Curve= 0 ,0
Exp/Cntr(USF)=0,0
Exp/Cntr=0.3,0.1

Type RM Length L Ch R = 1 ,6276    ,405.5,408.3,407.7
XS GIS Cut Line= 3
1653879.90560725510354.3790159751653938.08514639510597.440201713
1653803.62576705511026.675912698
#Sta/Elev= 30
       0  1102.5    57.2 1094.41   118.2 1087.75     152 1082.02   182.3 1074.14
   204.7 1071.53   215.6 1069.68   280.7 1067.17   346.1 1062.33     377 1061.47
   383.9 1060.76  389.791058.832   394.2 1057.59   397.6 1057.44   401.1 1057.56
  405.241058.834   421.7    1066   425.1 1067.01   438.9 1069.67     500 1087.66
   545.5 1098.63   559.2 1102.81   576.4 1106.18   593.6 1107.48   607.3  1109.8
   620.5 1110.89   638.3 1115.76   657.4 1118.51   676.1  1122.6   699.7 1130.69
#Mann= 5, -1 ,  0
       0     0.1       0  379.93    0.05       0  389.79   0.045       0
  405.24    0.05       0  419.93     0.1       0
Bank Sta=389.79,405.24
XS Rating Curve= 0 ,0
Exp/Cntr(USF)=0,0
Exp/Cntr=0.3,0.1

Type RM Length L Ch R = 1 ,5868    ,376,367.9,363.1
XS GIS Cut Line= 6
1653657.05181167510273.6148534071653579.95776102510547.017934459
1653555.39306672510597.4402017131653525.65685782510768.100183189
 1653511.4351927510810.7651785581653484.56461789510881.399794638
#Sta/Elev= 30
       0 1124.82    12.5 1121.05    36.4 1115.09    53.4 1109.52    60.2 1107.82
      67 1106.75    90.9 1106.01   162.5 1093.65   176.1 1090.63   179.7 1088.92
   182.9 1086.72   193.2 1077.77   202.9 1071.48     217 1063.23   223.8    1060
   227.2 1059.06   256.8  1057.2   278.1 1056.87  309.471053.667   318.1 1052.65
   322.7 1052.86  326.311053.667   332.1 1054.82   396.8 1060.21   469.9 1070.01
   495.9 1074.85   536.2 1086.08     557 1090.73   575.7 1094.06   633.9 1102.66
#Mann= 7, -1 ,  0
       0     0.1       0     100    0.05       0     160     0.1       0
  304.06    0.05       0  309.47   0.045       0  326.31    0.05       0
  558.37    0.06       0
Bank Sta=309.47,326.31
XS Rating Curve= 0 ,0
Exp/Cntr(USF)=0,0
Exp/Cntr=0.3,0.1

Type RM Length L Ch R = 1 ,5500    ,483.6,499.1,523.4
XS GIS Cut Line= 6
1653151.95570305510231.6868552271653167.57837522510330.904504567
1653206.20132947 510409.993257151653235.44405314510479.269365311
1653319.78738838510727.8502329741653333.90481421510822.951748803
#Sta/Elev= 30
       0  1108.6      28 1103.48    44.4 1099.25    61.3 1096.15    84.5 1093.67
   118.8 1094.49   131.1 1094.11   155.6 1090.79   192.4 1084.52   242.2  1072.4
   252.9 1066.62   256.5 1066.41   263.7 1068.01   270.3 1066.96   278.1 1062.89
   291.3 1051.46  298.891047.776   315.5 1046.58  318.691047.776   327.2 1051.31
   340.1 1051.51   353.7 1054.02   395.2 1058.64   443.7 1060.72   485.3 1065.46
     520 1072.52   546.6 1080.48     560 1083.23   586.6 1093.41   622.3 1098.81
#Mann= 4, -1 ,  0
       0     0.1       0  298.89   0.045       0  318.69     0.1       0
  383.65    0.05       0
Bank Sta=298.89,318.69
XS Rating Curve= 0 ,0
Exp/Cntr(USF)=0,0
Exp/Cntr=0.3,0.1

Type RM Length L Ch R = 1 ,5001    ,505.9,500.9,473.9
XS GIS Cut Line= 6
1653096.78586589510239.7645949721653003.26571172510435.661184818
1652940.07751788510483.3031498941652842.08755639510503.808686316
1652775.19333322510575.8377417331652664.89106038510769.078825057
#Sta/Elev= 30
       0 1105.81      31 1101.11   101.3 1087.64   165.3 1071.26   255.4 1055.79
   282.4  1052.6   297.2 1046.36   301.9 1045.13   328.7 1044.05   335.4 1042.64
  340.971040.327   345.4 1039.36  366.041040.325   375.2 1045.27     378 1045.67
   418.3 1047.47   453.3 1046.53   462.3 1047.53   471.7 1050.59   484.7 1055.92
   502.6  1064.4   521.3 1072.04   528.2 1074.33   540.1 1076.83   554.4 1077.68
   598.1 1077.85   620.7 1079.29   641.7 1081.37   694.3 1089.16   718.3 1091.82
#Mann= 5, -1 ,  0
       0     0.1       0  340.97   0.045       0  366.04     0.1       0
  605.65    0.05       0  666.71     0.1       0
Bank Sta=340.97,366.04
XS Rating Curve= 0 ,0
Exp/Cntr(USF)=0,0
Exp/Cntr=0.3,0.1

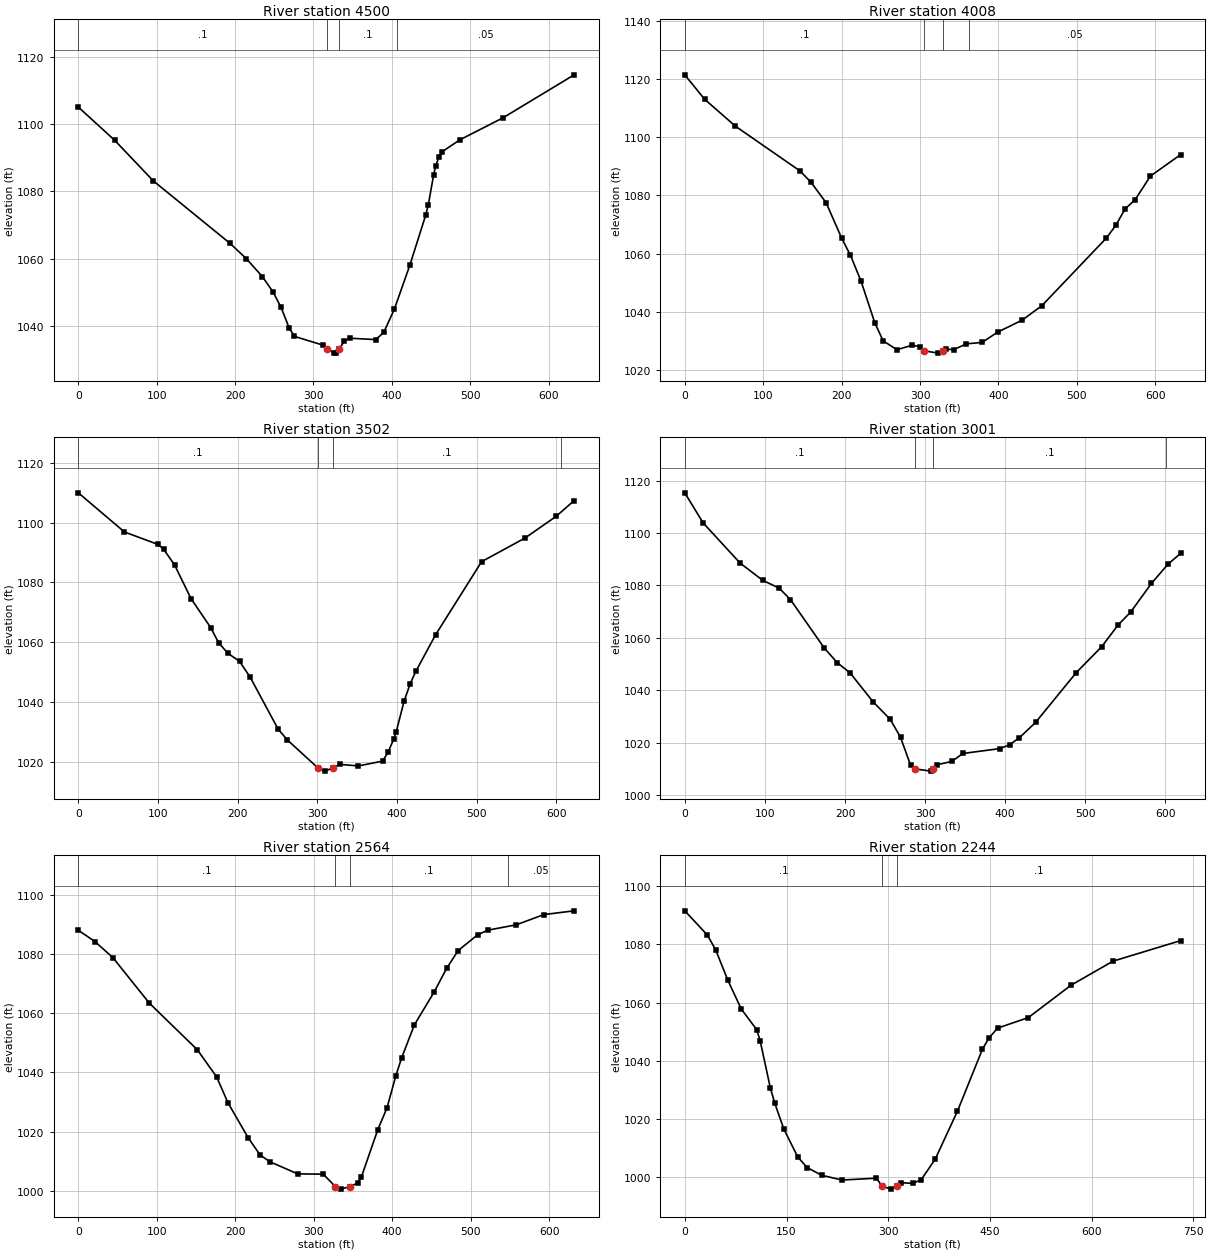
Type RM Length L Ch R = 1 ,4500    ,496.8,492.3,490.7
XS GIS Cut Line= 6
 1652568.5739958510134.0958430621652529.72466405510234.702597231
1652489.41437723510317.7641108931652469.08370923510391.330236733
1652448.91773905510489.2755788861652397.24002089510740.260641232
#Sta/Elev= 30
       0 1105.02    46.4 1095.17    95.6 1083.15   193.6  1064.6   214.5 1060.03
   234.9 1054.73   248.5 1050.18   258.7 1045.62     269 1039.52   275.8 1037.01
   312.6 1034.39  317.671033.364     326 1032.05   329.4  1032.2   333.11033.364
   339.4 1035.57   346.1 1036.48   379.6 1036.06   389.7 1038.19   403.2 1045.05
   423.2 1058.25   443.3    1073   446.6 1076.07   453.3 1084.82   455.9 1087.49
     460 1090.13   464.3  1091.8   486.8  1095.3   542.1 1101.87   632.7 1114.59
#Mann= 4, -1 ,  0
       0     0.1       0  317.67   0.045       0   333.1     0.1       0
   406.5    0.05       0
Bank Sta=317.67,333.1
XS Rating Curve= 0 ,0
Exp/Cntr(USF)=0,0
Exp/Cntr=0.3,0.1

Type RM Length L Ch R = 1 ,4008    ,484.8,505.9,509.6
XS GIS Cut Line= 6
1652151.97968464509934.4725546391652075.89551923510110.561769396
1652046.60194264 510186.314570651652046.03862356510286.612926483
 1652066.2856303510448.2648341511652056.49627981510543.763002723
#Sta/Elev= 30
       0 1121.56    25.2 1113.16    64.5 1103.88   146.7  1088.5     161 1084.55
   180.2  1077.5   200.1 1065.29   211.3 1059.38   224.8 1050.47   242.3 1036.14
   252.9 1029.96   270.5 1026.88   290.3 1028.47   300.2 1027.84  305.42 1026.49
   323.2 1025.71  329.61 1026.49     333  1027.1   342.8 1026.91   359.2 1028.91
     379 1029.39   398.9 1032.93   430.1 1037.05   455.2 1042.01   537.7 1065.37
   549.7 1069.74   561.6 1075.44     574 1078.44   593.8 1086.69   632.3 1094.08
#Mann= 4, -1 ,  0
       0     0.1       0  305.42   0.045       0  329.61     0.1       0
  363.04    0.05       0
Bank Sta=305.42,329.61
XS Rating Curve= 0 ,0
Exp/Cntr(USF)=0,0
Exp/Cntr=0.3,0.1

Type RM Length L Ch R = 1 ,3502    ,499.3,501.4,499.5
XS GIS Cut Line= 6
1651868.98353148509733.4063557241651757.11137989509879.611443892
1651701.51765905509930.8321419811651619.09328322509988.751973644
1651568.78203213510046.2387353031651470.38098222510203.669194728
#Sta/Elev= 30
       0 1109.92    57.9 1096.85     100 1092.69     107 1091.13   120.8 1085.87
   141.6 1074.55   166.2 1064.93   176.2 1059.83   187.8 1056.35   202.4 1053.65
   215.7  1048.4   250.8 1031.05   262.1 1027.49  301.011018.016   309.2 1016.99
  319.741018.017   328.1 1019.25   351.6 1018.73     382 1020.33   388.8 1023.23
   395.9  1027.6   399.1 1030.05     409 1040.32   416.8 1046.24   423.8 1050.32
   448.6 1062.52   506.4 1086.94   560.8 1094.81     600 1102.07   622.6 1107.34
#Mann= 4, -1 ,  0
       0     0.1       0  301.01   0.045       0  319.74     0.1       0
  606.54    0.05       0
Bank Sta=301.01,319.74
XS Rating Curve= 0 ,0
Exp/Cntr(USF)=0,0
Exp/Cntr=0.3,0.1

Type RM Length L Ch R = 1 ,3001    ,440.9,436.2,438.9
XS GIS Cut Line= 6
1651564.39358947509442.2212425621651357.68534148509594.051647559
1651279.12053797509655.9271799771651221.35917056509703.779118389
1651157.34355055509765.7281414721651093.97294238  509840.9835684
#Sta/Elev= 30
       0 1115.36    22.8  1103.9    69.1 1088.51    97.4 1081.92   117.8 1078.96
   131.9 1074.59   174.1  1056.1   190.5 1050.44   206.3 1046.62   235.1 1035.53
   256.5 1028.85   269.3 1022.01   281.8 1011.41  287.521009.931   306.9 1009.08
  310.431009.931   315.2 1011.55   333.2 1012.77   347.3 1015.83   393.9  1017.7
   405.5 1019.19   417.2 1021.69   437.9 1027.67   488.6 1046.67   520.6 1056.65
   540.9 1064.88   556.6 1069.81   582.6 1080.78   603.2  1088.1     619 1092.24
#Mann= 4, -1 ,  0
       0     0.1       0  287.52   0.045       0  310.43     0.1       0
  600.58    0.05       0
Bank Sta=287.52,310.43
XS Rating Curve= 0 ,0
Exp/Cntr(USF)=0,0
Exp/Cntr=0.3,0.1

Type RM Length L Ch R = 1 ,2564    ,318.5,320.2,316.1
XS GIS Cut Line= 6
1651174.96917617509230.4884778321651103.43979168509303.874157822
1651030.46552817509363.7464134161650968.35115109509412.073088413
1650901.43297784509486.3849476631650730.97268885509677.715273654
#Sta/Elev= 30
       0 1088.01    21.1  1084.2      44 1078.78    90.4 1063.41   151.6 1047.65
   176.2 1038.49   190.6 1029.78   216.3 1017.96   231.5 1012.15   243.9 1009.84
   279.4 1005.73   312.1 1005.62  327.52 1001.43   334.1 1000.57  346.16 1001.43
   356.1 1002.65   360.6 1004.61   381.6 1020.66   393.3 1028.01   404.6 1038.87
   411.8 1044.77   428.1    1056   453.7  1067.3   469.2  1075.1     484 1081.15
   508.7 1086.45   521.5 1088.02   558.2 1089.86   593.1  1093.3   631.8 1094.57
#Mann= 4, -1 ,  0
       0     0.1       0  327.52   0.045       0  346.16     0.1       0
  548.07    0.05       0
Bank Sta=327.52,346.16
XS Rating Curve= 0 ,0
Exp/Cntr(USF)=0,0
Exp/Cntr=0.3,0.1

Type RM Length L Ch R = 1 ,2244    ,380,383.2,388.9
XS GIS Cut Line= 3
1650924.54112441509000.4672408751650598.98671103509380.280723151
1650610.85588235509610.881765962
#Sta/Elev= 30
       0 1091.55    33.4  1083.2    45.6 1078.09    63.6 1067.62    83.2 1057.83
   106.1 1050.68   111.1  1046.9   126.2 1030.61   132.8 1025.33     146 1016.56
   166.5 1006.97   180.3  1003.3   201.9 1000.65   232.1     999   282.5  999.65
  291.05996.8624   304.2  995.88  312.48996.8625   318.6  998.12   335.9  997.85
   348.5  999.07   369.4 1006.24     402 1022.64   438.8  1043.9   448.5 1047.82
   461.2 1051.22   506.7 1054.86   569.4 1065.95   631.5 1074.25   731.2 1081.31
#Mann= 3, -1 ,  0
       0     0.1       0  291.05   0.045       0  312.48     0.1       0
Bank Sta=291.05,312.48
XS Rating Curve= 0 ,0
Exp/Cntr(USF)=0,0
Exp/Cntr=0.3,0.1

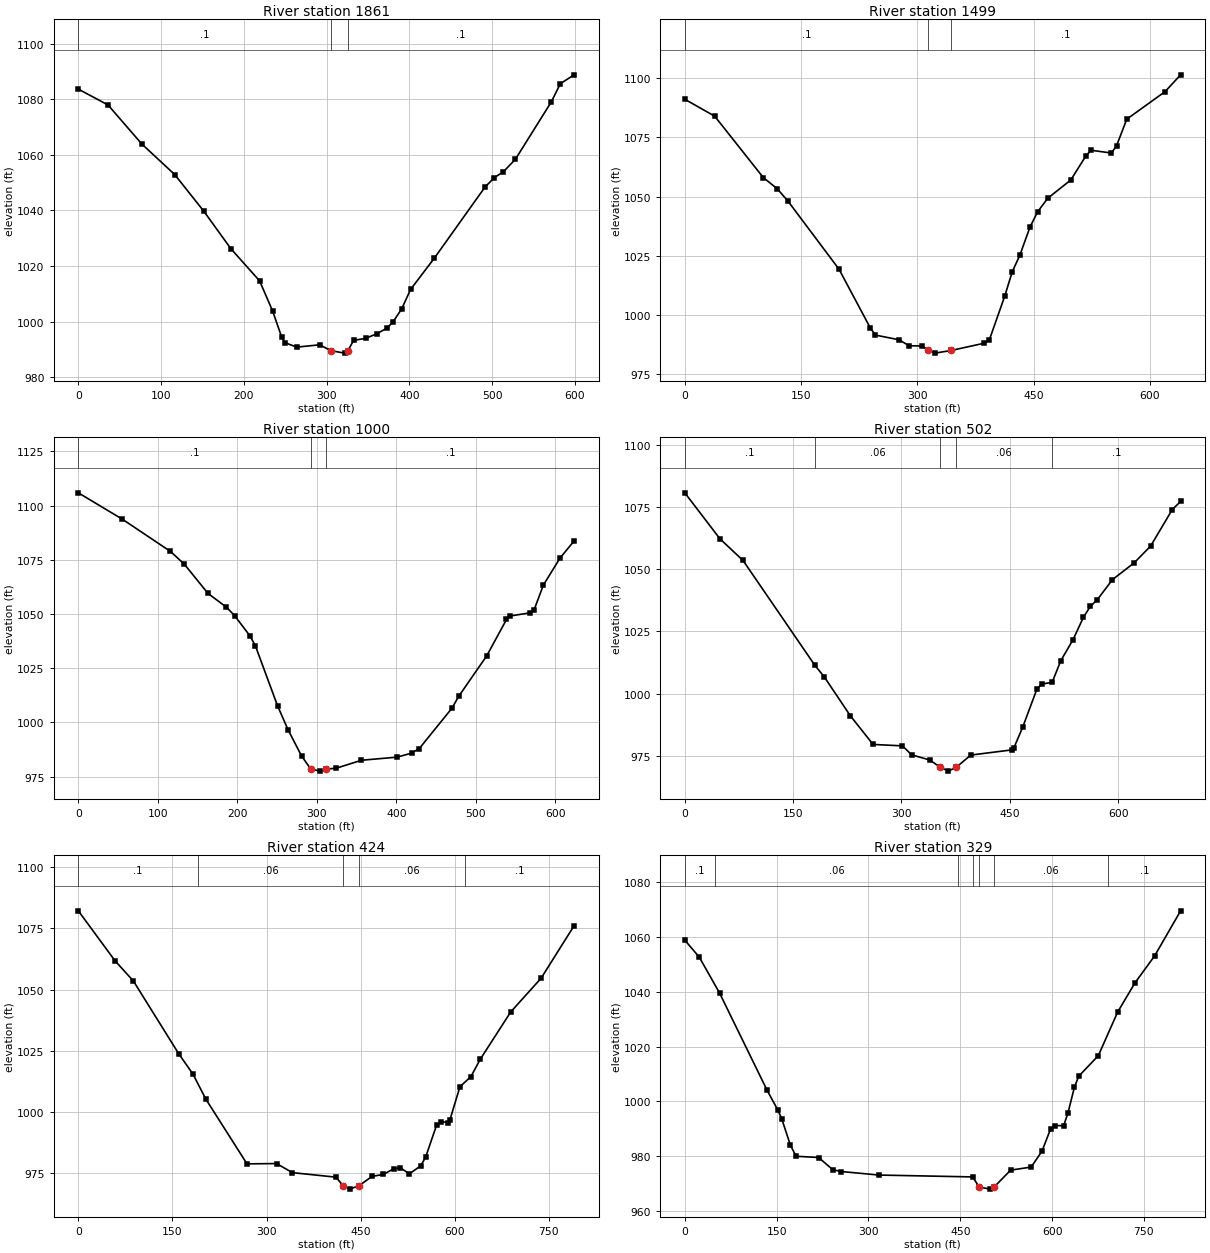
Type RM Length L Ch R = 1 ,1861    ,355.1,361.7,371.8
XS GIS Cut Line= 2
1650733.85172258508880.7514512981650190.73374557509133.950836419
#Sta/Elev= 30
       0 1083.68    35.9 1077.96    76.8 1063.89   116.4 1052.94   151.7  1039.7
   184.3 1026.25   219.1 1014.63   234.9 1003.72   245.8  994.36   249.7  992.41
   263.9   990.8   291.6  991.63  305.33989.5165   321.9  988.64  325.74 989.514
   332.7  993.24   347.2  993.95   360.8  995.63   372.5  997.56   379.8  999.68
   390.6 1004.46   401.5 1011.55   430.4  1022.9   491.6 1048.47   502.8 1051.82
   513.7 1053.94   528.2 1058.42   571.6 1079.09   582.5 1085.64   599.2 1088.82
#Mann= 3, -1 ,  0
       0     0.1       0  305.33   0.045       0  325.74     0.1       0
Bank Sta=305.33,325.74
XS Rating Curve= 0 ,0
Exp/Cntr(USF)=0,0
Exp/Cntr=0.3,0.1

Type RM Length L Ch R = 1 ,1499    ,512,499.3,482.9
XS GIS Cut Line= 6
1650609.17305897508641.2464665621650429.62322122508708.146595225
1650351.73558173508724.4536492231650250.68460272508703.358218983
1650172.51612389508700.3264008911649985.75731106508710.958597481
#Sta/Elev= 30
       0 1091.08    38.6 1083.93   101.3 1058.02   119.4 1053.25   133.3 1047.99
     199 1019.31   239.2  994.62   245.9   991.5   276.1  989.54   289.5     987
   306.2  986.87  314.01984.9917   322.8  983.88  343.51984.9898   386.4  988.07
     393   989.5   412.7  1007.8   422.5 1018.22   432.4 1025.27   445.5 1037.17
   455.4 1043.61   468.3 1049.27   498.1 1056.99   517.7 1067.24   524.3 1069.55
   550.6 1068.37   557.2 1071.51   570.3 1082.67   619.7  1094.3   639.8  1101.4
#Mann= 3, -1 ,  0
       0     0.1       0  314.01   0.045       0  343.51     0.1       0
Bank Sta=314.01,343.51
XS Rating Curve= 0 ,0
Exp/Cntr(USF)=0,0
Exp/Cntr=0.3,0.1

Type RM Length L Ch R = 1 ,1000    ,489.8,498.2,502.3
XS GIS Cut Line= 6
 1650280.9329018508012.3618975581650160.67690872508238.522206396
1650113.56545439508326.7392215581650078.50646938  508393.0868579
1650018.29727222508461.6687417331649939.31481864508524.807066888
#Sta/Elev= 30
       0 1105.88    55.2 1093.75   115.9 1078.84   133.4 1072.92   163.1 1059.47
   186.2 1053.14   196.6 1049.22   215.7 1039.95   222.6 1035.39   250.6 1007.59
   263.8  996.55   280.8  984.47  292.37978.4495   304.4   977.5  312.08978.4499
   324.5  978.86     356  982.51     401  983.96   419.1   985.8   428.8   987.9
   469.9 1006.54   478.6 1012.12   513.5 1030.61   538.5 1047.45   543.2 1049.08
   567.9  1050.5   573.3 1051.99   584.9 1063.33   605.9 1075.82   623.6 1083.71
#Mann= 3, -1 ,  0
       0     0.1       0  292.37   0.045       0  312.08     0.1       0
Bank Sta=292.37,312.08
XS Rating Curve= 0 ,0
Exp/Cntr(USF)=0,0
Exp/Cntr=0.3,0.1

Type RM Length L Ch R = 1 ,502     ,76.1,77.7,80.2
XS GIS Cut Line= 6
1650141.39370665507921.4520235451649896.18063626507887.969114335
1649808.53419745507933.2695209131649767.17295666507958.874098544
1649744.52275337507965.7676386751649612.56069943508199.163211694
#Sta/Elev= 30
       0 1080.76    48.7 1062.25    80.6 1053.55     180  1011.4   193.1 1006.71
   229.3  991.03   260.7  979.52   301.4  978.94   314.2  975.33   339.1  973.27
  353.88970.3276   364.9  968.78  375.97970.3277     396  975.24   452.8  977.32
   455.7  978.14   467.9  986.44   487.5 1001.72   494.2 1003.81   508.7  1004.5
   520.6 1013.18   537.6 1021.66     552 1030.68   561.6 1035.06   571.3 1037.79
   592.2 1045.83   622.4 1052.62     645 1059.32   675.1 1074.05   686.6 1077.29
#Mann= 5, -1 ,  0
       0     0.1       0     180    0.06       0  353.88   0.045       0
  375.97    0.06       0  508.47     0.1       0
Bank Sta=353.88,375.97
XS Rating Curve= 0 ,0
Exp/Cntr(USF)=0,0
Exp/Cntr=0.3,0.1

Type RM Length L Ch R = 1 ,424     ,102.2,95.3,85.4
XS GIS Cut Line= 5
 1650159.1199527507890.9234886771649795.73190863507865.318911046
1649713.00942706507903.7257774931649682.48089219507908.649734729
1649559.38196127508186.360922879
#Sta/Elev= 30
       0 1082.21    58.3 1061.85    87.9 1053.46   160.3 1023.66   182.8 1015.42
     203 1005.32   268.8  978.77   315.9  978.89   341.2  975.18   410.5  973.33
  422.03  969.88   432.7  968.44  447.67969.8796     468  973.64   486.2  974.45
   502.6  976.79   513.4  977.11   527.7   974.7   545.7  977.98   553.5  981.52
     571  994.64     578  996.07   588.7  995.67   592.3  996.85   608.2 1010.33
   625.6 1014.41   640.5 1021.51   689.2  1040.9   737.5 1054.65   790.2 1076.16
#Mann= 5, -1 ,  0
       0     0.1       0     190    0.06       0  422.03   0.045       0
  447.67    0.06       0  616.42     0.1       0
Bank Sta=422.03,447.67
XS Rating Curve= 0 ,0
Exp/Cntr(USF)=0,0
Exp/Cntr=0.3,0.1

Type RM Length L Ch R = 1 ,329     ,,,
XS GIS Cut Line= 4
1650104.69995642507869.4662553911649701.32181838507820.336866785
1649657.36394437507830.6798959651649522.90456502508162.949708384
#Sta/Elev= 30
       0  1058.8    23.6 1052.62    56.7 1039.56   134.6    1004   152.3  996.75
   158.2  993.76   172.3  984.19   181.7  980.01   218.6  979.56   241.8  975.11
   255.4  974.45   317.3  973.16   470.2  972.48  480.88968.8255   498.5  968.03
  505.43968.8246   532.3  974.95   565.8  976.07   583.5  981.86   597.8  990.11
   604.7  991.21   618.9  991.15   625.9  995.76   636.5 1005.21   643.6 1009.21
   675.5 1016.68   707.3 1032.67   735.6 1043.28   767.5 1053.05     810 1069.49
#Mann= 7, -1 ,  0
       0     0.1       0      50    0.06       0  446.36     0.1       0
  471.52    0.06       0  480.88   0.045       0  505.43    0.06       0
  691.52     0.1       0
Bank Sta=480.88,505.43
XS Rating Curve= 0 ,0
Exp/Cntr(USF)=0,0
Exp/Cntr=0.3,0.1
LCMann Table=0

Chan Stop Cuts=-1
Use User Specified Reach Order=0
Composite Channel Slope=5